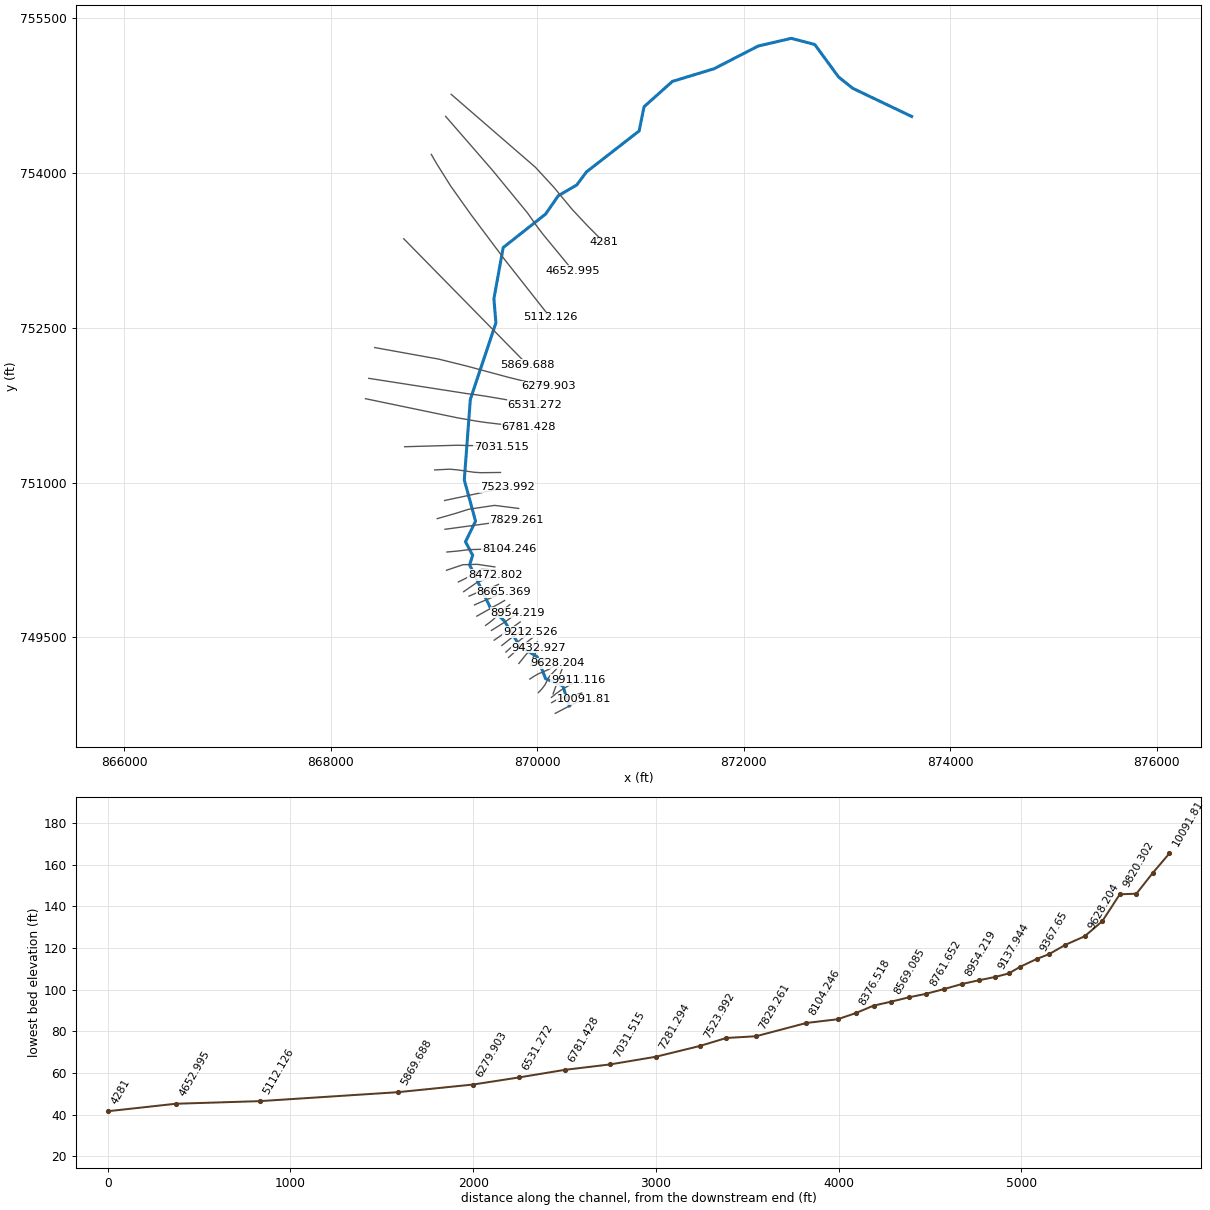
--- 9111_ras.prj (project) ---

Proj Title=9111
Current Plan=p01
Default Exp/Contr=0.3,0.1
English Units
Geom File=g01
Flow File=f01
Plan File=p01
Y Axis Title=Elevation
X Axis Title(PF)=Main Channel Distance
X Axis Title(XS)=Station
BEGIN DESCRIPTION:
RFD model 9111 exported to HEC-RAS
END DESCRIPTION:

--- 9111_ras.p01 (plan) ---

Plan Title=Plan 01
Program Version=4.10
Short Identifier=Plan 01
Geom File=g01
Flow File=f01
Subcritical Flow
Calc Critical at every XS
Secant Critical Depth

--- 9111_ras.f01 (steady flow) ---

Flow Title=Flow 01
Program Version=5.01
Number of Profiles= 6
Profile Names=10yr,25yr,50yr,100yr,100plus,500yr
River Rch & RM=9111,34,10091.81
  154.09  243.38  325.75   399.8  583.71 1014.79
River Rch & RM=9111,34,8276.476
  158.93  251.04  336.03  412.43  602.15 1042.28
River Rch & RM=9111,34,8104.246
  166.27   262.7   351.7  431.72  630.31 1084.21
River Rch & RM=9111,34,7829.261
  173.99  274.95  368.17  451.97  659.88 1127.94
River Rch & RM=9111,34,7666.614
  228.64   362.1  485.69   596.9  871.47 1435.29
River Rch & RM=9111,34,7523.992
  233.03  369.09   495.1   608.5   888.4 1459.33
River Rch & RM=9111,34,7281.294
  238.63     378  507.09  623.24  909.94  1489.7
River Rch & RM=9111,34,7031.515
  248.86  394.29  529.06  650.33  949.48 1545.47
River Rch & RM=9111,34,6781.428
  727.39 1151.37 1545.38 1896.91 2769.49 3858.21
River Rch & RM=9111,34,6531.272
  789.66 1251.71 1681.73 2065.91 3016.22 4158.51
River Rch & RM=9111,34,6279.903
   807.4 1280.15 1720.27 2113.54 3085.77 4241.92
River Rch & RM=9111,34,5869.688
  813.42 1289.85 1733.44 2129.84 3109.57 4270.54
River Rch & RM=9111,34,5112.126
  820.04  1300.5 1747.89 2147.75 3135.71 4301.93
Boundary for River Rch & Prof#=9111,34,1
Up Type= 0
Dn Type= 2
Boundary for River Rch & Prof#=9111,34,2
Up Type= 0
Dn Type= 2
Boundary for River Rch & Prof#=9111,34,2
Up Type= 0
Dn Type= 2
Boundary for River Rch & Prof#=9111,34,2
Up Type= 0
Dn Type= 2
Boundary for River Rch & Prof#=9111,34,2
Up Type= 0
Dn Type= 2
Boundary for River Rch & Prof#=9111,34,2
Up Type= 0
Dn Type= 2

--- 9111_ras.g01 (geometry) ---

Geom Title=9111
Program Version=4.10

River Reach=9111,34
Reach XY= 30
870312.445034093748836.547807687870248.889288722749031.170907825
 870081.78859426749101.700421693869999.583733162749313.809796731
869835.000399828749412.420907865869682.222622047749661.032019169
869548.791023381749785.240752918869346.675747042750202.525074539
869376.265670241750295.818508868869306.663907503750426.500334633
869404.079093695750625.901452021869295.018323538751025.216936432
869353.584954534751804.831702154869601.137119792752545.712852921
869581.781607741752779.456942211869671.475196172753274.874924354
870082.454103527753599.646023642870205.406431288753777.188176521
870383.495770188753880.375190381870478.808270231754008.500190287
870988.303035391754404.557813074871035.383086256754638.519216128
871310.220564945754883.914602913871713.704103559755006.590468055
872140.787436871755226.208523555872461.099936919755300.861301319
872688.327786427755241.248008847872918.431408343754927.221849234
873056.021818132754816.943108061873627.165540518754544.154266019

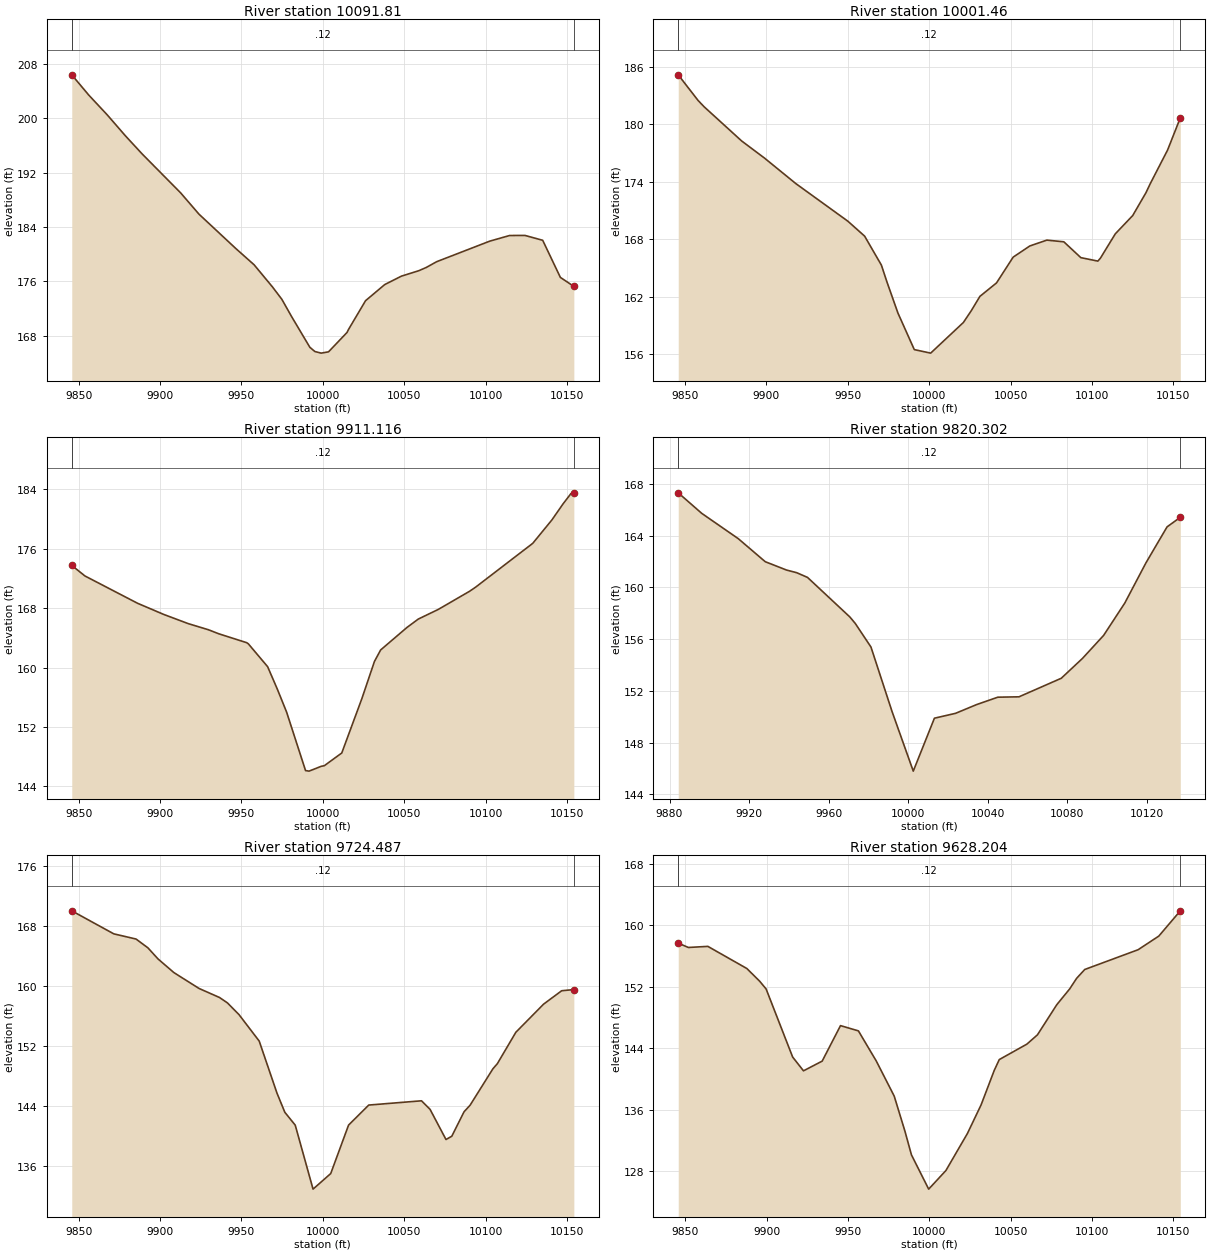
Type RM Length L Ch R = 1 ,10091.81,90.345400,90.345400,90.345400
XS GIS Cut Line= 6
 870175.72402561748764.954473693870284.562742576748821.922170312
870311.073160728748836.891265761870312.788492198748837.919681057
870339.549706399748852.422604523870452.614206683748900.440702698
#Sta/Elev= 30
9845.709206.37379856.179203.38699867.466200.49229878.753197.37799888.936194.7397
9912.614189.00619923.901185.86749946.475180.82669957.762178.42289969.058175.1624
9974.815173.34379980.542170.91319992.026166.28219995.153165.6533    9999165.4208
10003.52165.610510014.89168.464610015.86168.930710026.26173.132810038.03175.5047
10048.22176.739910059.09177.557210063.61178.030610069.95 178.87310102.55181.8943
10114.78 182.72810124.28182.739710135.14182.0253   10146176.565510154.28175.2394
#Mann= 3 , 0 , 0
9845.709    0.12       09845.709    0.12       010154.28    0.12       0
#XS Ineff= 2 , 0
       0                               0
Bank Sta=9845.709,10154.28
Exp/Cntr=0.3,0.1

Type RM Length L Ch R = 1 ,10001.46,90.345400,90.345400,90.345400
XS GIS Cut Line= 6
870141.304694337 748868.89490038870182.927363708748893.145120844
870224.996527382748911.081738355870258.124994258748919.329870169
870343.315427328748931.778325175870432.312789734748962.534446827
#Sta/Elev= 30
9845.804185.15669857.932182.49539861.654181.83189884.801178.24889898.705176.4814
9917.971173.81669950.018169.88249960.323168.32279970.629165.29549973.849 163.632
9980.768160.30239990.833156.480910000.89156.114110020.99 159.31110025.84 160.542
10031.15162.038610041.35163.441810051.56166.1292 10061.8167.296810072.25167.9061
 10082.7167.730410093.15 166.07910103.61165.717310105.16166.018110114.31168.5601
10125.02170.471810133.16172.855310135.72173.773110146.43177.302810154.26180.6682
#Mann= 3 , 0 , 0
9845.804    0.12       09845.804    0.12       010154.26    0.12       0
#XS Ineff= 2 , 0
       0                               0
Bank Sta=9845.804,10154.26
Exp/Cntr=0.3,0.1

Type RM Length L Ch R = 1 ,9911.116,90.814400,90.814400,90.814400
XS GIS Cut Line= 6
870138.647475707748919.920980464870190.710152175748961.178124068
870228.466052609748988.039563188870263.239255932749008.820286132
870310.143885371749035.610156408 870396.53270475749088.459887991
#Sta/Elev= 30
9845.726 173.7619853.832172.33789886.106168.66879902.207167.16379917.419165.9132
9929.692165.10059935.997164.56099953.247163.35559954.237163.20519966.102160.1241
9972.059157.10369977.752154.01659989.402146.13849991.553146.0642    9999146.7108
10000.95146.796510011.66 148.50510024.02155.828210031.73160.821810035.55162.3763
 10051.8165.419610058.71166.537710071.01167.838510090.18170.273610093.88170.8243
10129.05176.733910140.77179.871910147.66 182.043 10152.5183.426210154.29183.5322
#Mann= 3 , 0 , 0
9845.726    0.12       09845.726    0.12       010154.29    0.12       0
#XS Ineff= 2 , 0
       0                               0
Bank Sta=9845.726,10154.29
Exp/Cntr=0.3,0.1

Type RM Length L Ch R = 1 ,9820.302,95.814600,95.814600,95.814600
XS GIS Cut Line= 2
870154.726458664748953.870633714870240.597082836749191.263459881
#Sta/Elev= 24
 9884.37167.31329896.205165.72329914.573163.76649928.107161.98769938.741161.3447
9943.971161.13369949.376 160.7719970.644157.71539973.369157.21369981.278155.3878
9991.912150.383410002.55145.788210013.18149.881710023.81150.258110034.45150.9379
10045.08151.507210055.72151.535710076.98152.971610087.62154.504410098.25156.2832
10108.89158.783410119.52161.890710130.16164.679910136.82165.4186
#Mann= 3 , 0 , 0
 9884.37    0.12       0 9884.37    0.12       010136.82    0.12       0
#XS Ineff= 2 , 0
       0                               0
Bank Sta=9884.37,10136.82
Exp/Cntr=0.3,0.1

Type RM Length L Ch R = 1 ,9724.487,96.283400,96.283400,96.283400
XS GIS Cut Line= 6
870013.102208044748966.100826611870047.925031358749003.480646156
870074.966632401749038.808914195870110.428517023749108.708655052
870122.261906043749126.775148817870200.305926562749208.071810045
#Sta/Elev= 30
 9845.77169.9773  9871.6166.90599885.267166.21369892.566  165.04 9898.77163.5616
9908.497161.74349923.957159.6257 9936.55158.41759941.412157.69899948.555156.1275
9960.939152.6041 9971.84145.67089976.674143.11429983.072141.39359994.012132.8644
10004.87134.940310015.83141.401810028.23 144.07510060.65144.643610065.89143.5086
10075.69139.480110079.27139.9216 10086.8 143.18410090.47144.047310104.55148.9215
10107.24149.592810118.62153.784510135.66157.533810146.77159.319710154.24159.4726
#Mann= 3 , 0 , 0
 9845.77    0.12       0 9845.77    0.12       010154.24    0.12       0
#XS Ineff= 2 , 0
       0                               0
Bank Sta=9845.77,10154.24
Exp/Cntr=0.3,0.1

Type RM Length L Ch R = 1 ,9628.204,105.074600,105.074600,105.074600
XS GIS Cut Line= 6
869929.800115698 749097.46114831 869972.24543516749125.432371874
870010.614845383749147.086783913870110.478727601749189.104125235
870141.610723651749209.362289028870195.481265169749250.819313282
#Sta/Elev= 30
9845.738157.66519851.966157.09969863.942157.24189887.894154.36099895.786 152.704
9899.734151.69959916.038142.8366  9922.7141.03869934.182142.30179945.453146.9249
9956.454146.23969967.454142.30859978.446137.74869985.021133.19439989.043 130.097
9999.629125.636910010.21128.057310023.45132.886810031.85 136.61310039.92141.0967
10043.01142.505110059.94144.509610066.46 145.72410078.39149.661810086.28151.7067
10090.55153.086110095.52154.231910128.31156.805610141.03158.580910154.25161.8708
#Mann= 3 , 0 , 0
9845.738    0.12       09845.738    0.12       010154.25    0.12       0
#XS Ineff= 2 , 0
       0                               0
Bank Sta=9845.738,10154.25
Exp/Cntr=0.3,0.1

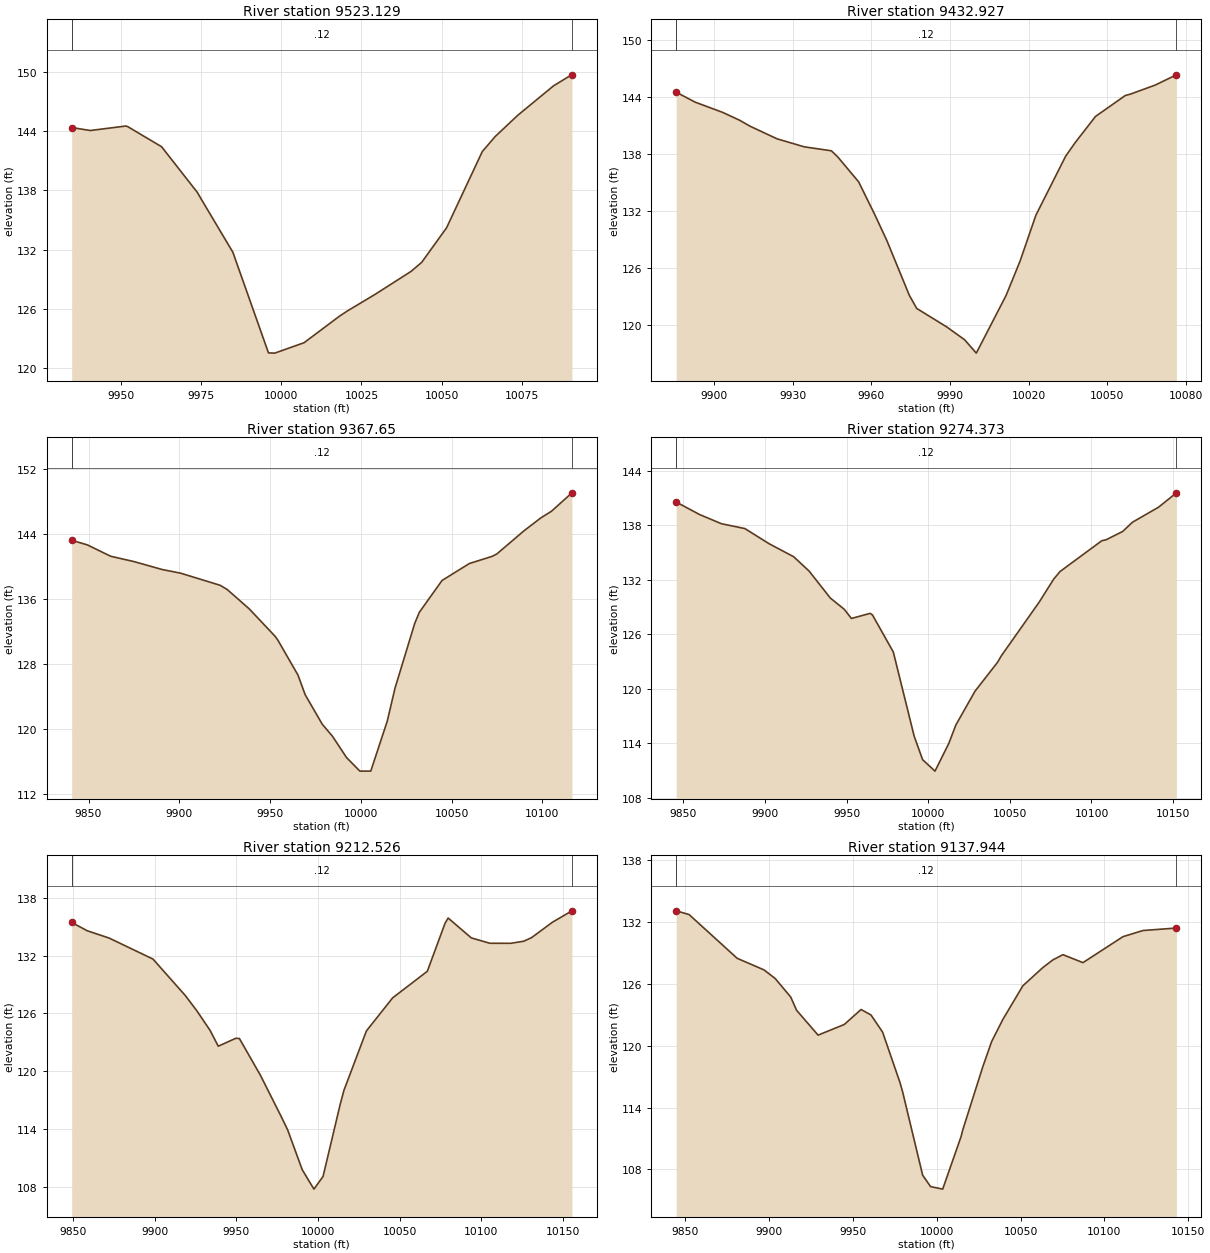
Type RM Length L Ch R = 1 ,9523.129,90.201800,90.201800,90.201800
XS GIS Cut Line= 2
869949.761673122749227.368376562870090.184697623 749295.44369774
#Sta/Elev= 23
9934.601144.35399940.422144.05369951.535144.50839952.095144.44439962.649 142.413
9973.762137.81369975.019137.11599984.875131.75389995.988121.57519997.943121.5489
 10007.1122.601910018.21125.302310020.87125.865510029.33127.506310040.44 129.806
10043.79130.728810051.55134.221410062.67141.918210066.71143.446910073.78145.6022
10084.89148.563910089.64149.507110090.65149.6829
#Mann= 3 , 0 , 0
9934.601    0.12       09934.601    0.12       010090.65    0.12       0
#XS Ineff= 2 , 0
       0                               0
Bank Sta=9934.601,10090.65
Exp/Cntr=0.3,0.1

Type RM Length L Ch R = 1 ,9432.927,65.276900,65.276900,65.276900
XS GIS Cut Line= 3
869938.533845311749227.986973981869958.759174645749300.908791993
870013.226669815749402.168271188
#Sta/Elev= 27
9885.635144.46679892.913143.41389903.291142.34859909.829141.51339913.668140.9054
9924.046139.56459934.423138.72159944.801138.30059947.245137.65079955.178135.0381
 9961.31131.60239965.956128.85189974.484123.1152 9977.31121.72769988.665119.7992
9995.594118.428110000.02117.027610011.38123.0967 10016.7126.701610022.73131.5277
10034.08137.738510037.81 139.20110045.44 141.91110056.79144.112910058.92144.2762
10068.15145.206510076.29146.2897
#Mann= 3 , 0 , 0
9885.635    0.12       09885.635    0.12       010076.29    0.12       0
#XS Ineff= 2 , 0
       0                               0
Bank Sta=9885.635,10076.29
Exp/Cntr=0.3,0.1

Type RM Length L Ch R = 1 , 9367.65,93.277400,93.277400,93.277400
XS GIS Cut Line= 3
869823.731930165749248.275909577869893.929934078749335.476910505
870002.473817257749457.920936397
#Sta/Elev= 30
9840.734143.26879849.366142.69999862.203141.30069875.041 140.6459890.597139.6639
9900.716139.21689922.491137.72469926.392137.20579938.438  134.849952.679131.4689
9954.292130.97469965.405126.65869969.367124.23869978.769120.60529984.442 119.111
9992.132116.50199999.517114.8266 10005.5114.831110014.59120.997210018.86125.0616
10029.67133.004910032.22134.386410044.74138.311810059.82140.406710072.31141.2833
10074.89141.575510089.97144.449910099.04146.004910105.04146.845810116.31 149.114
#Mann= 3 , 0 , 0
9840.734    0.12       09840.734    0.12       010116.31    0.12       0
#XS Ineff= 2 , 0
       0                               0
Bank Sta=9840.734,10116.31
Exp/Cntr=0.3,0.1

Type RM Length L Ch R = 1 ,9274.373,61.847300,61.847300,61.847300
XS GIS Cut Line= 4
869724.352115771749306.875652513869785.127872127749361.454943873
869813.731406063 749384.87821433869960.793703778749501.765948514
#Sta/Elev= 30
9845.534140.54559859.845139.17119873.286138.15649887.626137.62469902.593135.9459
9917.559134.52519927.048132.9374 9939.98129.98679948.599128.73389952.905127.7356
9964.386128.29899965.811128.12159978.585124.04869991.359114.79439996.529112.2049
10004.13110.9445 10012.6113.997810016.91116.020910028.67119.743310042.45122.9129
10044.74123.6199   10068129.542610076.89132.074210080.78132.905410106.32 136.284
10109.03136.3977 10119.1137.3042 10125.1 138.31910141.17139.983210152.05141.5552
#Mann= 3 , 0 , 0
9845.534    0.12       09845.534    0.12       010152.05    0.12       0
#XS Ineff= 2 , 0
       0                               0
Bank Sta=9845.534,10152.05
Exp/Cntr=0.3,0.1

Type RM Length L Ch R = 1 ,9212.526,74.581200,74.581200,74.581200
XS GIS Cut Line= 4
869697.930454352749358.473709874869758.706183842749413.052932325
869787.309704193749436.476172142869934.371930627749553.363751754
#Sta/Elev= 30
9849.041135.43629858.543134.57459871.984133.81519898.865131.63479918.675 127.852
9925.746126.2673  9933.8124.24999938.862122.59739949.584123.41879951.787123.3999
9964.712119.57569977.521115.26669981.397113.90839990.295109.78749997.468107.7733
10003.07109.094610013.54116.552510015.84118.015910029.61124.178910045.68127.6089
10066.94130.370110077.83135.361710079.71135.8898 10093.9133.831810105.26 133.276
10118.03133.271110126.04133.488510130.81133.858210143.58135.455210155.55  136.64
#Mann= 3 , 0 , 0
9849.041    0.12       09849.041    0.12       010155.55    0.12       0
#XS Ineff= 2 , 0
       0                               0
Bank Sta=9849.041,10155.55
Exp/Cntr=0.3,0.1

Type RM Length L Ch R = 1 ,9137.944,87.441800,87.441800,87.441800
XS GIS Cut Line= 3
869658.969476131749422.217790383869754.938481492749499.277678591
869901.640676637749595.412961648
#Sta/Elev= 30
9844.509133.07319852.243132.71099880.896128.47139896.868127.35179903.542126.5204
 9912.84124.72139916.367123.43059929.192121.02149944.783122.05159954.841123.5066
9960.755122.97489967.661121.31949978.027 116.4379979.617115.52749991.572107.4456
9996.272106.340110003.53106.091410014.52111.197910015.48111.817310027.44117.9458
10032.76120.4093 10039.4122.533910051.35125.803710063.31127.575610069.25128.3132
10075.26128.821710087.22128.051210111.13130.571610123.09131.166110142.98131.4036
#Mann= 3 , 0 , 0
9844.509    0.12       09844.509    0.12       010142.98    0.12       0
#XS Ineff= 2 , 0
       0                               0
Bank Sta=9844.509,10142.98
Exp/Cntr=0.3,0.1

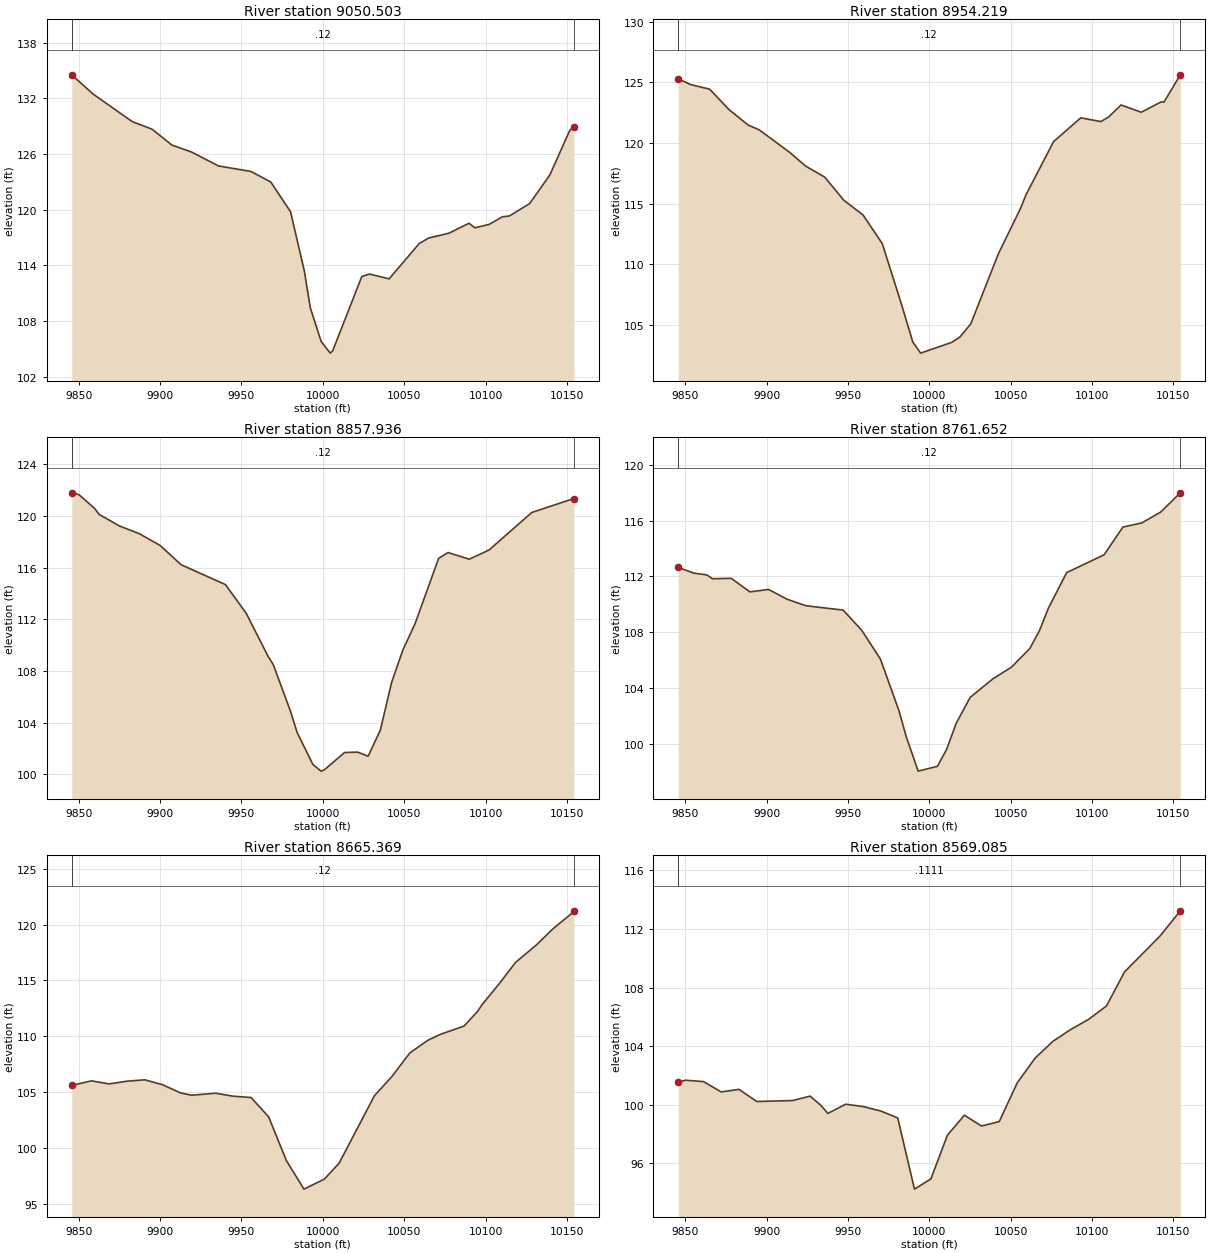
Type RM Length L Ch R = 1 ,9050.503,96.283500,96.283500,96.283500
XS GIS Cut Line= 5
 869584.42861719749473.713975729869710.486990655749560.906332657
869712.048728275749562.155722761869760.309377713749594.734164551
869836.918524882749650.985673244
#Sta/Elev= 30
9845.725134.53279858.579132.49389882.897129.48629895.056128.67429907.215126.9671
9919.374126.2071 9935.88124.70899955.851124.1154 9968.01122.97989980.169119.7717
9988.617113.40169992.328109.4056    9999105.781510004.56104.527310006.08104.7801
10023.96112.784710028.69113.054610040.76 112.53710059.23116.340310065.05116.9358
10077.45117.453110089.86118.530410093.47118.036410102.27118.410410110.36119.2258
10114.67119.315710127.08 120.64710139.48123.718410151.89128.591710154.27128.8832
#Mann= 3 , 0 , 0
9845.725    0.12       09845.725    0.12       010154.27    0.12       0
#XS Ineff= 2 , 0
       0                               0
Bank Sta=9845.725,10154.27
Exp/Cntr=0.3,0.1

Type RM Length L Ch R = 1 ,8954.219,96.283500,96.283500,96.283500
XS GIS Cut Line= 5
 869558.61007099749568.679609511869688.654938222749649.822818405
 869690.30739291749650.949492058869700.993152259749658.125109721
869814.395807057749740.926866642
#Sta/Elev= 30
9845.716125.28099853.248124.82089865.035 124.4369876.822122.76369888.609121.4861
9895.437121.08699914.327119.2143 9923.97118.09939935.757117.18319947.544115.2713
9959.331114.05939971.118111.69859982.905106.70619989.889103.58729994.692102.6729
10013.87103.563710018.83104.001510025.53105.087910042.49110.870710055.98114.5719
10059.45 115.728 10076.4120.112210093.12122.072910105.51121.765210110.32122.1551
10117.89123.134510130.27122.536510142.65123.397110144.24123.366910154.29125.6194
#Mann= 3 , 0 , 0
9845.716    0.12       09845.716    0.12       010154.29    0.12       0
#XS Ineff= 2 , 0
       0                               0
Bank Sta=9845.716,10154.29
Exp/Cntr=0.3,0.1

Type RM Length L Ch R = 1 ,8857.936,96.283500,96.283500,96.283500
XS GIS Cut Line= 6
869501.383754952749616.822611764869535.000195677749641.129006121
869566.708410755749666.676503672869620.247410393749716.420071782
869677.203838739749771.111081551869735.158963605749817.605570685
#Sta/Elev= 30
9845.716121.77319850.178121.62599859.672120.57939862.519 120.1099874.859 119.219
9887.199118.61489900.041117.70359912.883116.21579940.143114.68019952.895112.4681
9966.549109.08879969.515108.50249980.204104.86529984.201103.25429993.858100.7806
9998.887100.2597   10001100.367410013.39101.699310021.45101.728310027.83 101.408
10035.32  103.4210042.26107.109210049.18109.6191 10056.7111.661710071.14116.6979
10076.91117.159410089.96116.640810102.16117.352810128.42120.252910154.26121.3332
#Mann= 3 , 0 , 0
9845.716    0.12       09845.716    0.12       010154.26    0.12       0
#XS Ineff= 2 , 0
       0                               0
Bank Sta=9845.716,10154.26
Exp/Cntr=0.3,0.1

Type RM Length L Ch R = 1 ,8761.652,96.283500,96.283500,96.283500
XS GIS Cut Line= 6
869416.576440296749706.413127115869536.877833745749773.875880271
  869549.9594302749781.943160981869559.816581451749788.229286601
869634.996234855749828.110772813 869685.36819181749857.834236685
#Sta/Elev= 30
9845.705112.64099855.362112.2314 9863.26112.10619866.827111.83079878.292111.8608
9889.757110.88899901.223111.06469912.688110.35939924.153109.89729947.083109.5843
9958.548108.13039970.013 106.0679981.478102.34369985.772100.54099993.17398.05138
10005.0398.39641 10010.799.6233510016.56101.477910025.14103.3341 10039.2104.6691
10050.52105.496210061.84 106.84410067.82108.136610073.16109.710910084.48112.2737
10107.41113.542410119.03115.533910130.64115.828810142.25116.609310154.29117.9843
#Mann= 3 , 0 , 0
9845.705    0.12       09845.705    0.12       010154.29    0.12       0
#XS Ineff= 2 , 0
       0                               0
Bank Sta=9845.705,10154.29
Exp/Cntr=0.3,0.1

Type RM Length L Ch R = 1 ,8665.369,96.283500,96.283500,96.283500
XS GIS Cut Line= 6
869394.001876569749815.098956151869452.892230687749841.460542685
869534.762117662749875.769010071869536.669282995749876.371272809
869581.444491508749895.228903389 869675.83774938749940.503716879
#Sta/Elev= 30
9845.711105.5886 9857.76105.99839868.717105.72629879.673105.96689890.629106.0909
9901.585105.64759912.517104.9189 9919.39104.70959934.203104.89149945.045104.6215
9955.888104.5065 9966.73 102.7699977.57398.860749988.41596.29976   1000197.20326
10010.0498.6289610031.74104.669710042.59106.409510053.53108.509510064.62109.6367
10072.18 110.158 10086.8110.9077 10095.3112.254810097.89112.826810108.98114.8038
10118.42116.604510131.16118.158910141.55 119.63310153.34121.039310154.27121.2279
#Mann= 3 , 0 , 0
9845.711    0.12       09845.711    0.12       010154.27    0.12       0
#XS Ineff= 2 , 0
       0                               0
Bank Sta=9845.711,10154.27
Exp/Cntr=0.3,0.1

Type RM Length L Ch R = 1 ,8569.085,96.283500,96.283500,96.283500
XS GIS Cut Line= 6
 869340.83101593  749899.7238807869447.457857117749946.637100793
869470.253120087749953.743739417869497.735779509749957.652972161
869517.189820262749964.328158866 869626.24177687750013.924053488
#Sta/Elev= 29
9845.753101.54869850.308101.67639861.233101.58459872.158100.87849883.083101.0537
9894.008100.22429915.859100.28729926.784100.59049933.34899.970319937.70999.41084
9948.634100.03869959.55999.876179970.14499.577039980.61999.105149990.91594.24203
   1000194.9381510011.1297.9167710021.5799.2874210032.1498.5494310043.0498.85617
10054.02101.490110065.01103.183210075.99 104.33410086.98 105.14410097.96105.8349
10108.95 106.75410119.94109.065110141.91111.536310154.26113.2418
#Mann= 3 , 0 , 0
9845.753  0.1111       09845.753  0.1111       010154.26  0.1111       0
#XS Ineff= 2 , 0
       0                               0
Bank Sta=9845.753,10154.26
Exp/Cntr=0.3,0.1

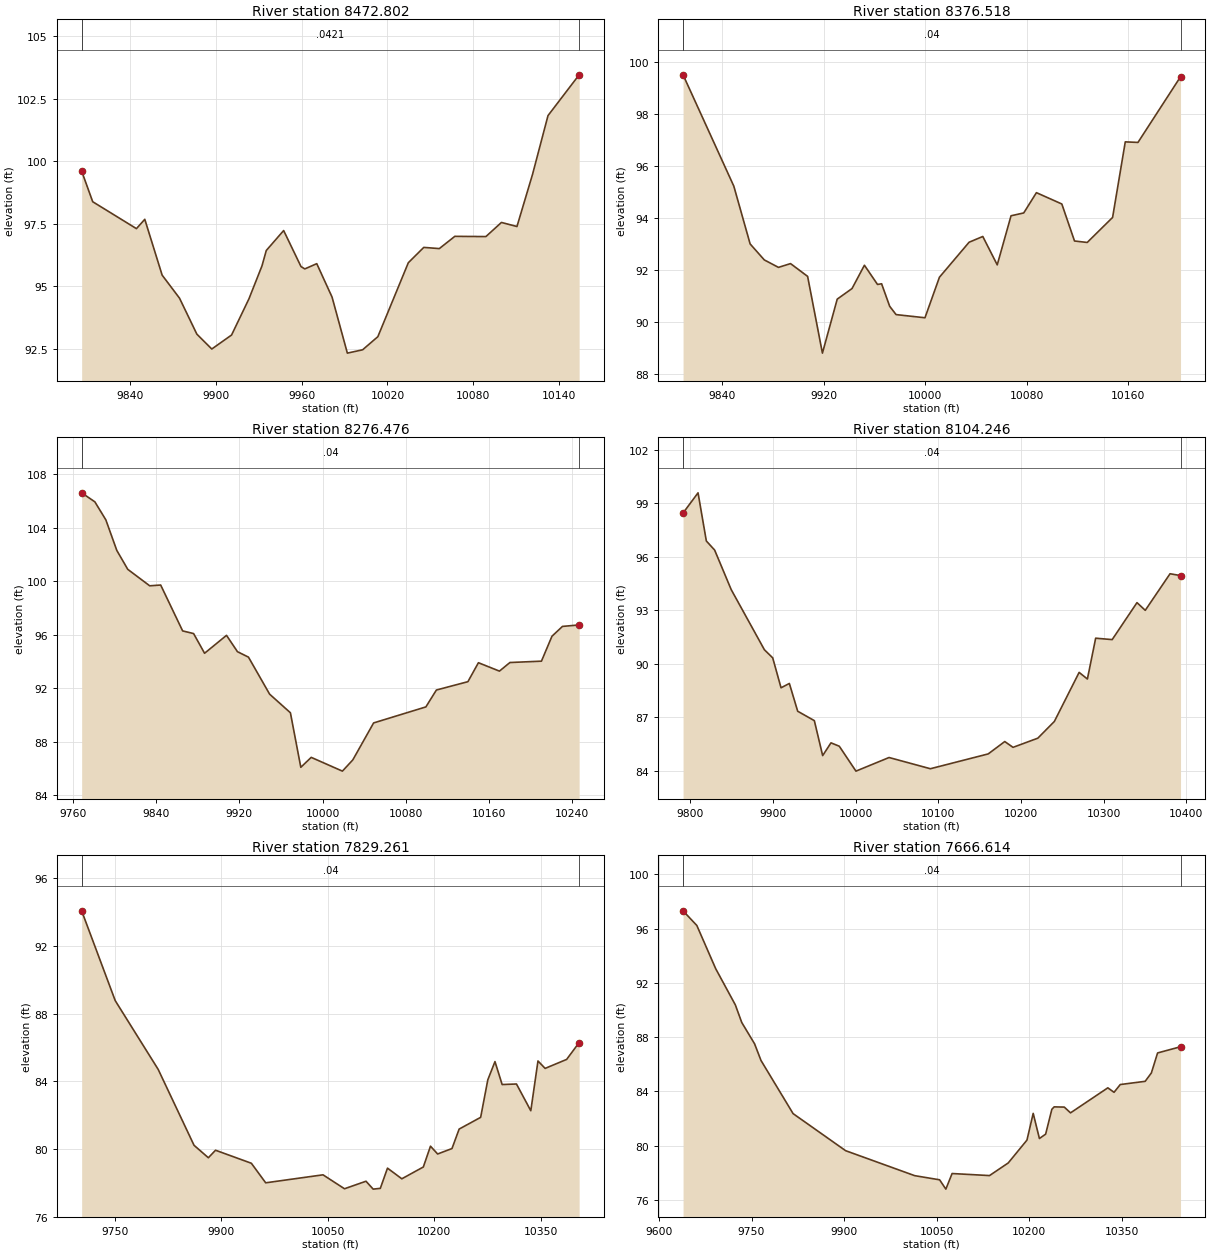
Type RM Length L Ch R = 1 ,8472.802,96.283500,96.283500,96.283500
XS GIS Cut Line= 6
869288.634184432749943.182490262869417.195944862750032.052361441
 869451.56370835750045.289190809869453.461074941750045.921646329
869487.963119617 750058.81906333869595.045201672750104.602847365
#Sta/Elev= 30
9805.88399.603069813.62298.378499844.252 97.30259850.092 97.67579862.24895.44278
9874.40594.522129886.56293.08259 9897.0192.487449910.87593.047669923.03294.49365
9932.18395.814649935.18896.428819947.34597.226549959.50295.784659962.17195.69164
9970.53495.90116 9981.2594.564519991.96692.3230810002.6492.4559210013.3292.98077
10034.67 95.939610045.49 96.552510056.3696.5038910067.2496.9943610088.9996.98472
10099.87 97.550110110.7497.3873810121.6299.4663510132.49101.823910154.29103.4546
#Mann= 3 , 0 , 0
9805.883  0.0421       09805.883  0.0421       010154.29  0.0421       0
#XS Ineff= 2 , 0
       09953.932                       0
Bank Sta=9805.883,10154.29
Exp/Cntr=0.3,0.1

Type RM Length L Ch R = 1 ,8376.518,100.042300,100.042300,100.042300
XS GIS Cut Line= 6
869237.650473115750037.193682146869312.196408471 750074.23754906
869372.212264785750110.316332076  869373.9174684750111.361456488
869461.290888831750159.074042726869598.531055868750154.406914337
#Sta/Elev= 30
 9808.9799.494329848.98495.211329861.84492.98985 9873.0192.374739884.17792.08869
9893.69392.233819907.152 91.7415 9918.8288.790249930.48890.866979942.15691.27409
 9951.9292.170839962.239 91.43219965.47291.45764 9971.8390.592969976.86690.27242
9999.65490.1502310011.0591.7084310034.4393.0553310045.2393.2765810056.6292.18545
 10067.594.0728710077.5194.1819910087.5194.9620210107.5394.5265110117.5393.10333
10127.5493.0464410147.5594.0086710157.55 96.915510167.5696.8944510201.1199.42104
#Mann= 3 , 0 , 0
 9808.97    0.04       0 9808.97    0.04       010201.11    0.04       0
#XS Ineff= 2 , 0
       0 9976.54                       0
Bank Sta=9808.97,10201.11
Exp/Cntr=0.3,0.1

Type RM Length L Ch R = 1 ,8276.476,172.229700,172.229700,172.229700
XS GIS Cut Line= 4
869122.969469479750150.679516646869281.269195047750204.126542408
869418.686025609 750208.27907192869590.868784274750183.013661622
#Sta/Elev= 30
9768.233106.59489780.931105.92149791.486104.5768 9802.04102.29069812.595100.8761
9833.70499.644769844.25999.703359865.36896.275219875.92396.075369886.47794.60341
9907.58695.942919918.14194.719239928.69694.314599949.049 91.54759969.05990.15481
9979.06386.080369989.06886.8220310019.0885.7940410029.0986.63309 10049.189.39592
10099.39  90.59410109.4991.8550210139.8292.4802810149.9293.8965810170.1493.26845
10180.2493.9117410210.5794.0127710220.6795.8745210230.7896.6103910246.8296.72024
#Mann= 3 , 0 , 0
9768.233    0.04       09768.233    0.04       010246.82    0.04       0
#XS Ineff= 2 , 0
       09940.539                       0
Bank Sta=9768.233,10246.82
Exp/Cntr=0.3,0.1

Type RM Length L Ch R = 1 ,8104.246,274.985100,274.985100,274.985100
XS GIS Cut Line= 6
869126.945023274750327.225524406 869232.55271035750336.839238482
869289.580797453 750343.95922193869291.565456412750344.206473585
869345.119721029750350.593270634869727.702929107750360.682273224
#Sta/Elev= 30
9791.01998.449629809.14899.57983 9819.1996.882569829.23196.375239849.31494.15837
9889.47990.792569899.52990.338349909.60788.662869919.685 88.90529929.762 87.3501
9949.91886.823449959.99384.864579970.064 85.58019980.13585.3896410000.2883.99615
10040.3684.7580510090.3884.13019 10160.484.9601810180.4185.6524910190.41 85.3275
10220.4285.8407210240.4386.7768410270.4489.5246810280.4489.1532810290.45 91.4399
10310.4591.3610510340.4693.4312510350.4793.0005910380.4895.0483210393.1894.94579
#Mann= 3 , 0 , 0
9791.019    0.04       09791.019    0.04       010393.18    0.04       0
#XS Ineff= 2 , 0
       0                10134.26       0
Bank Sta=9791.019,10393.18
Exp/Cntr=0.3,0.1

Type RM Length L Ch R = 1 ,7829.261,162.647600,162.647600,162.647600
XS GIS Cut Line= 2
869108.187176081750547.299257103869802.448015238750641.923824703
#Sta/Elev= 30
9703.35794.074889750.60388.769619811.157 84.7027 9861.6280.220039881.80579.48277
9891.89779.926759942.35979.158159962.54478.0019210043.2878.4737210073.5677.65072
10103.8478.0952910113.9377.6286810124.02  77.67510134.1278.86863 10154.3 78.2394
10184.5878.9365710194.6780.1658210204.7679.7050810224.9580.0273610235.04 81.1771
10265.32 81.869710275.4184.08788 10285.585.16502 10295.683.8092510315.7883.84155
10335.9782.2606410346.0685.2014710356.1584.7633510386.4385.2934710404.0486.28922
#Mann= 3 , 0 , 0
9703.357    0.04       09703.357    0.04       010404.04    0.04       0
#XS Ineff= 2 , 0
       09913.554        10154.66       0
Bank Sta=9703.357,10404.04
Exp/Cntr=0.3,0.1

Type RM Length L Ch R = 1 ,7666.614,142.621500,142.621500,142.621500
XS GIS Cut Line= 5
869033.555496787750650.420913393869211.671757158 750701.47247264
869337.825065882750741.274787412869588.512223445750778.861443975
869821.897789898750749.052376782
#Sta/Elev= 30
9638.99797.306589661.30596.22664 9691.9193.03959 9723.7290.375249734.12389.07582
9754.92887.502869765.331  86.2769817.34482.359479902.47979.6283910014.3877.78817
10054.8377.4819910064.94  76.79510075.05 77.944710135.72 77.793310166.0678.72461
10196.3980.4071610206.5182.37761 10216.680.5258210226.6880.8481310236.76 82.6786
10240.5482.8579610256.9282.84044   1026782.4153810327.4984.2607710337.5783.93061
10347.6584.5036810387.9884.7400510398.0685.3574210408.1486.8318710445.3487.28844
#Mann= 3 , 0 , 0
9638.997    0.04       09638.997    0.04       010445.34    0.04       0
#XS Ineff= 2 , 0
       09942.093        10158.16       0
Bank Sta=9638.997,10445.34
Exp/Cntr=0.3,0.1

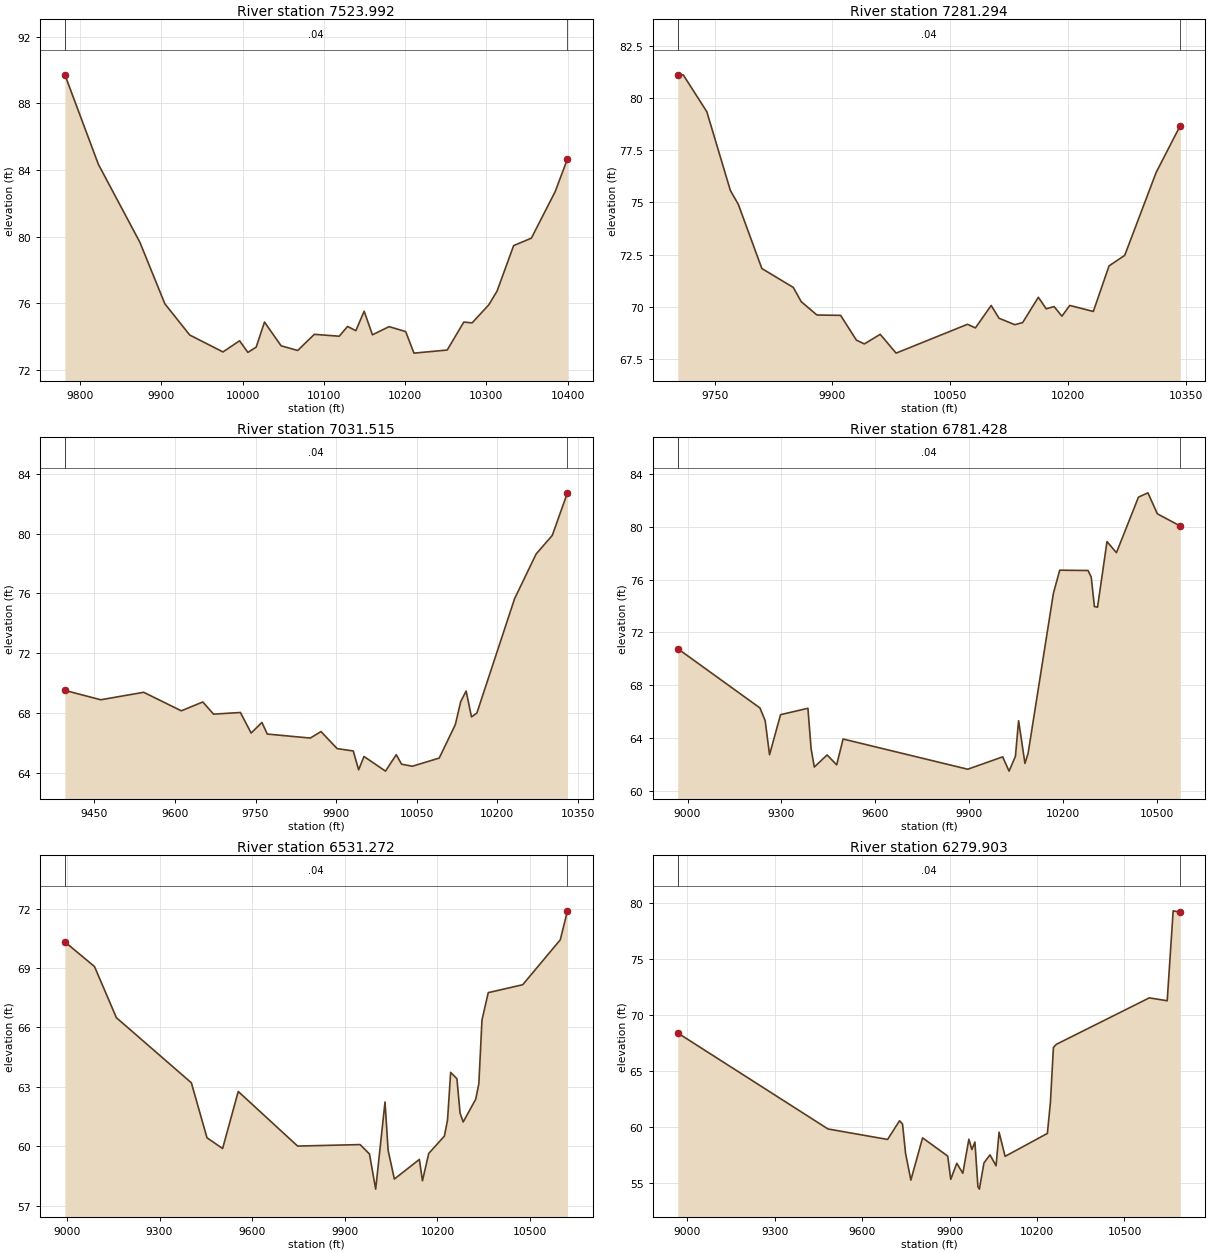
Type RM Length L Ch R = 1 ,7523.992,242.698300,242.698300,242.698300
XS GIS Cut Line= 2
869104.683657059750826.220429775869709.779547772750954.187417801
#Sta/Elev= 30
9781.29389.709249822.50184.334229873.60779.65375 9904.2775.966649934.93474.08885
9975.81973.074769996.26173.7446710006.4873.04678 10016.773.3638410026.9274.86854
10047.3773.4422110067.8173.1626410088.2574.1311910118.9274.0177210129.1474.60454
10139.3674.3493110149.5875.51957 10159.874.1014610180.2474.5939910200.6874.29674
10210.9173.0028710251.7973.1883710272.2374.8669110282.4574.81931 10302.9 75.8979
10313.1276.7233510333.5679.4574910355.3779.9039510384.6782.6955810399.77 84.6581
#Mann= 3 , 0 , 0
9781.293    0.04       09781.293    0.04       010399.77    0.04       0
#XS Ineff= 2 , 0
       09941.672        10105.92       0
Bank Sta=9781.293,10399.77
Exp/Cntr=0.3,0.1

Type RM Length L Ch R = 1 ,7281.294,249.778500,249.778500,249.778500
XS GIS Cut Line= 6
869008.040170995751122.068513526869154.573828192751129.283936594
869225.319029528751122.976123277869390.797747396751099.365017117
869457.687539352751095.213658966869645.742480357751097.543024468
#Sta/Elev= 30
9702.94781.090839709.91681.105929739.95279.340469769.98875.566329780.00174.91399
9810.037 71.83729850.08770.932529860.12670.252979880.20669.611339910.32569.59585
9930.469 68.41039940.57668.228469960.78968.688139981.00367.7881510071.9669.16796
10082.0368.9953810102.0970.0692710112.1169.4576410132.1569.1493410142.1769.24998
 10162.270.46125 10172.269.90895 10182.270.01559 10192.269.55652 10202.270.06963
 10232.269.78222 10252.271.96176 10272.272.4683410312.2176.4334310342.9578.67842
#Mann= 3 , 0 , 0
9702.947    0.04       09702.947    0.04       010342.95    0.04       0
#XS Ineff= 2 , 0
       0                10097.18       0
Bank Sta=9702.947,10342.95
Exp/Cntr=0.3,0.1

Type RM Length L Ch R = 1 ,7031.515,250.086900,250.086900,250.086900
XS GIS Cut Line= 6
868718.400020128 751346.70995802869227.077233707751361.107343514
869322.051055351751358.609085445  869324.0505617751358.564652036
869439.657423574751356.511359069869653.177000543751341.637289695
#Sta/Elev= 30
9395.11269.514769461.73968.887249541.77169.387579611.79968.147749651.81568.73986
9671.82367.925729721.84368.035799741.85166.659689761.85967.370749771.86366.59269
9851.89566.323819871.90366.758479901.91565.618849931.92665.461959941.92964.20191
9951.933 65.09139991.94764.1116310011.9565.2107210021.9564.5743110041.9664.43902
10091.9664.9852110121.9867.22573   1013268.7657710142.0369.4707310152.0567.73969
10162.0868.0004210232.2575.6478910272.3478.6418410302.4279.8865710330.6682.73573
#Mann= 3 , 0 , 0
9395.112    0.04       09395.112    0.04       010330.66    0.04       0
#XS Ineff= 2 , 0
       09787.141        10134.25       0
Bank Sta=9395.112,10330.66
Exp/Cntr=0.3,0.1

Type RM Length L Ch R = 1 ,6781.428,250.156700,250.156700,250.156700
XS GIS Cut Line= 6
868337.991804575751811.834917186869228.469687029751626.689426925
869418.510035575751593.712957924869506.201208944751580.871434991
869681.004563026751560.430098771869917.850379708751535.835244567
#Sta/Elev= 30
8968.80770.768699231.31166.274329248.00665.311349261.95362.728679297.13165.76452
9384.51966.248999394.73363.181619404.94761.793659445.80262.712699476.44461.96076
9496.87163.91914 9895.0661.6280110006.6762.56709   1002761.4843410047.3362.60467
10057.4965.3035910077.7862.0704610087.8962.8405810168.7174.9714610188.8576.71929
10279.4676.6945710289.5376.18943 10299.673.9623710309.6673.9166610339.8678.88657
10370.0278.04742 10440.482.2593110470.5682.5849810500.7280.9949110573.96 80.0666
#Mann= 3 , 0 , 0
8968.807    0.04       08968.807    0.04       010573.96    0.04       0
#XS Ineff= 2 , 0
       09639.716        10059.23       0
Bank Sta=8968.807,10573.96
Exp/Cntr=0.3,0.1

Type RM Length L Ch R = 1 ,6531.272,251.368600,251.368600,251.368600
XS GIS Cut Line= 6
868370.349963877752008.836996712869321.418684004751860.904362328
869374.830919723 751854.03785557 869413.38616596751849.346442163
869515.274989504751833.821697054 869977.81910247751755.103337855
#Sta/Elev= 30
8993.64970.323289089.43669.079889160.27766.496729403.15963.20603 9453.7660.42911
 9504.3659.885589554.96162.767559747.24360.009399949.65860.08416 9979.9359.60934
10000.0957.8340410030.3262.23571 10040.459.7928110060.5958.3446910141.5259.33316
10151.6358.2565510171.9259.6362810222.6460.5136710232.78 61.324210242.9363.73312
10263.2163.4094910273.36 61.6755 10283.561.2264210324.0862.3756610334.2263.16169
10344.3666.3770310364.6567.7602910476.2368.1603810597.9670.4300310621.1171.89397
#Mann= 3 , 0 , 0
8993.649    0.04       08993.649    0.04       010621.11    0.04       0
#XS Ineff= 2 , 0
       09675.351        10029.17       0
Bank Sta=8993.649,10621.11
Exp/Cntr=0.3,0.1

Type RM Length L Ch R = 1 ,6279.903,410.215200,410.215200,410.215200
XS GIS Cut Line= 6
868427.957715531752306.830456336869046.457131185752195.241158287
869315.489789996752128.539562439869728.120348785752017.328285743
869863.283534272751984.111225412870108.875886199751930.982331655
#Sta/Elev= 30
8967.87368.391059483.10259.81281  9687.458.875959728.52960.544299738.81160.24812
9749.13257.634359767.35655.243389807.48859.018919893.75557.388179904.11255.30934
9924.82856.743489945.54455.85251 9966.2658.896289976.61757.973969986.97558.64596
9997.33354.6473910002.2754.4357110018.0556.7766110038.7657.4976410059.4756.52138
10069.8359.5248910090.5457.3637710235.5359.4154910245.8962.1674310256.2467.09964
 10266.667.3822110585.0871.5301810646.4771.2710810666.9379.3088710691.3679.17738
#Mann= 3 , 0 , 0
8967.873    0.04       08967.873    0.04       010691.36    0.04       0
#XS Ineff= 2 , 0
       09821.874        10027.73       0
Bank Sta=8967.873,10691.36
Exp/Cntr=0.3,0.1

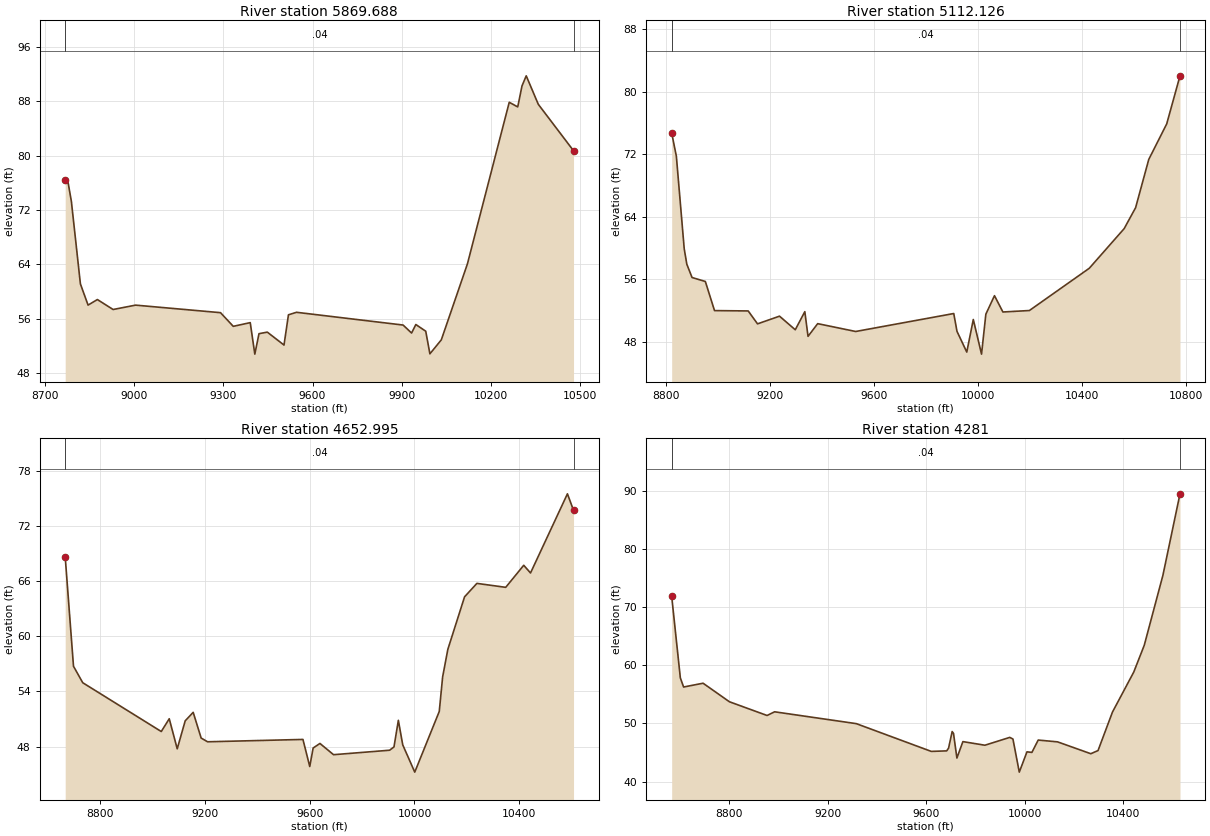
Type RM Length L Ch R = 1 ,5869.688,757.561800,757.561800,757.561800
XS GIS Cut Line= 2
868709.220544732753359.842805506869906.397494309752140.474591898
#Sta/Elev= 30
8768.56376.439978776.81376.416958789.36473.264618819.63461.12654 8845.4257.99197
8876.72958.813478929.504 57.34519005.19457.98877 9290.6756.878329333.49154.86598
9390.58655.411039405.982 50.77089419.99653.783969448.02454.01101 9504.0852.10789
9519.05156.564979546.12256.933419904.44455.055159932.99153.875199947.26555.13212
9980.557 54.14739994.57150.8143710032.9152.87279 10120.7 64.067410261.2987.87286
10289.8487.1937510304.1190.2814810318.3891.7738510358.9487.5780110477.3980.73705
#Mann= 3 , 0 , 0
8768.563    0.04       08768.563    0.04       010477.39    0.04       0
#XS Ineff= 2 , 0
       09857.075                       0
Bank Sta=8768.563,10477.39
Exp/Cntr=0.3,0.1

Type RM Length L Ch R = 1 ,5112.126,459.131000,459.131000,459.131000
XS GIS Cut Line= 6
  868976.0429749754176.860339677869027.213342182754087.602812009
869163.239836223 753870.93250283869357.950370188753596.341943468
869690.237314123753153.148575242870126.233925045752600.045473969
#Sta/Elev= 30
8823.34974.712398841.35871.74225  8871.659.910768881.57157.944878901.67756.24896
8952.78455.739068988.02352.021569117.45351.978229153.31550.329169237.756  51.311
9298.35649.575729335.07451.887049347.42948.733959384.49250.356099530.506 49.3545
9907.47751.648019919.96349.370219957.51246.724979982.58650.8842510014.2446.46349
10030.8251.5627210063.9853.9275710096.3651.8448710198.1552.0317310428.2857.42608
10562.4262.4908110606.3865.1660710656.9471.32982 10725.975.8665610776.97 82.0046
#Mann= 3 , 0 , 0
8823.349    0.04       08823.349    0.04       010776.97    0.04       0
#XS Ineff= 2 , 0
       09945.596        10057.11       0
Bank Sta=8823.349,10776.97
Exp/Cntr=0.3,0.1

Type RM Length L Ch R = 1 ,4652.995,371.995000,371.995000,371.995000
XS GIS Cut Line= 6
 869114.22744817754545.614407925869567.352812578754024.287951133
869908.385108941753608.552376586870004.070058512753472.424731216
870059.967803787753399.828695336870349.829178979753048.197529772
#Sta/Elev= 30
8665.42468.662698697.08956.748338732.48554.953189032.44949.636879062.93651.02773
9093.42347.75234 9123.9150.800669154.39851.727119184.88548.923119209.46448.51825
9573.81548.77422 9599.7945.823819612.778 47.84239638.75448.336119690.704 47.1119
9904.93847.597949921.63547.958589938.33250.855869955.07248.18686   1000145.21197
10094.6351.8230710107.5655.5955810127.4258.59209 10191.364.3127810238.4765.77911
10348.5265.34771 10417.467.7508710443.32 66.912710584.3475.5376710607.6573.73912
#Mann= 3 , 0 , 0
8665.424    0.04       08665.424    0.04       010607.65    0.04       0
#XS Ineff= 2 , 0
       09545.692        10146.19       0
Bank Sta=8665.424,10607.65
Exp/Cntr=0.3,0.1

Type RM Length L Ch R = 1 ,    4281,0.000000,0.000000,0.000000
XS GIS Cut Line= 6
869168.392921349754758.460449433 869983.65823875754052.561323736
870160.170736069 753860.98023566 870339.59043452753644.461497363
870485.099696758753488.979720212870647.390320166753325.825419635
#Sta/Elev= 30
8567.02371.914568602.21857.840148615.44556.275198694.52556.927338801.46453.73377
8954.23351.371828984.78752.00626 9316.51 49.96659620.74545.187169683.41445.27753
9690.96645.752089705.49648.605079710.98148.287789724.76444.043799749.08746.87271
9838.40246.252349939.37247.600419952.23747.316389977.96841.6190110009.1545.11105
10029.1845.0152410054.7347.1396810133.3946.8295710268.2944.7880910297.5645.33158
 10356.151.9525810442.5558.8459310485.0963.4441110560.9275.5094710630.2889.53925
#Mann= 3 , 0 , 0
8567.023    0.04       08567.023    0.04       010630.28    0.04       0
#XS Ineff= 2 , 0
       09454.017                       0
Bank Sta=8567.023,10630.28
Exp/Cntr=0.3,0.1